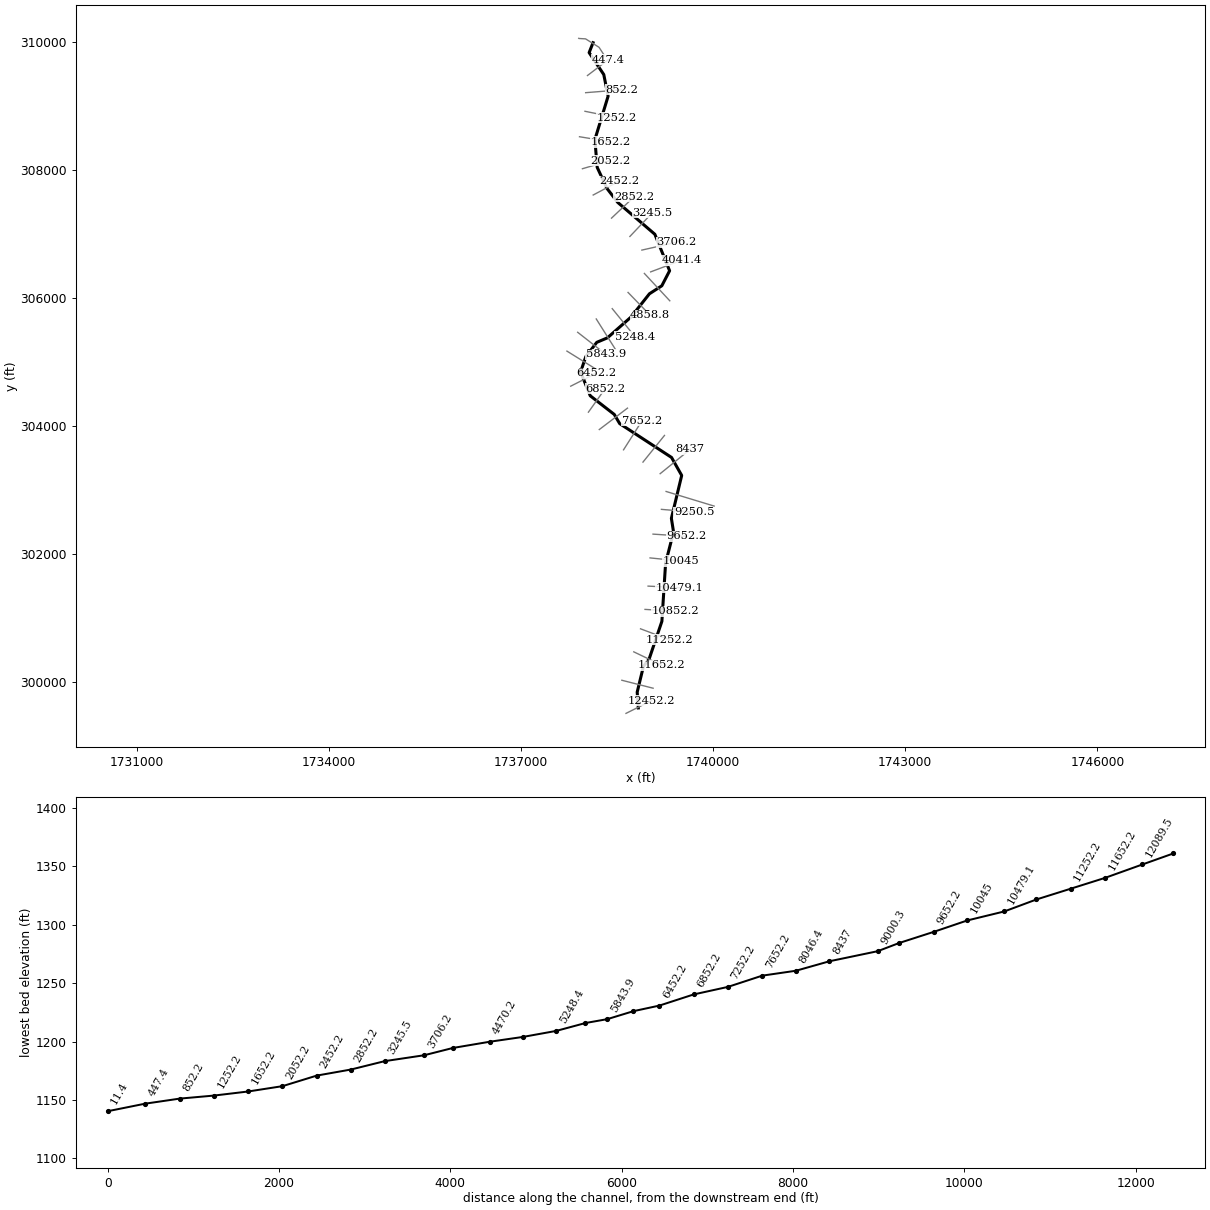
--- BRUSHYFRK.prj (project) ---

Proj Title=BRUSHYFRK
Current Plan=p01
Default Exp/Contr=0,0
English Units
Geom File=g01
Flow File=f01
Plan File=p01
BEGIN DESCRIPTION:
END DESCRIPTION:
DSS Export Rating Curves= 0
DSS Export Rating Curve Sorted= 0
DSS Export Volume Flow Curves= 0
DXF OffsetX= 0
DXF OffsetY= 0
DXF ScaleX= 0
DXF ScaleY= 0

--- BRUSHYFRK.p01 (plan) ---

Plan Title=Floodplain
Program Version=4.00
Geom File=g01
Flow File=f01
K Sum by GR=0
Std Step Tol=0.01
Critical Tol=0.01
Num of Std Step Trials=20
Max Error Tol=0.3
Flow Tol Ratio=0.001
Split Flow NTrial=30
Split Flow Tol=0.02
Split Flow Ratio=0.02
Log Output Level=0
Friction Slope Method=1
Unsteady Friction Slope Method=2
Unsteady Bridges Friction Slope Method=1
Global Log Level=0
CheckData=False
Run HTab=0
Run UNet=0
Run PostProcess=0
UNET Theta=0
UNET Theta Warmup=0
UNET ZTol=0
UNET ZSATol=0
UNET MxIter=0
UNET MaxInSteps=0
UNET DtIC=0
UNET DtMin=0
UNET MaxCRTS=0
UNET WFStab=0
UNET SFStab=0
UNET WFX=0
UNET SFX=0
UNET DSS MLevel=0
UNET DZMax Abort=0
UNET Convert EG Bridges=0
UNET Use Existing IB Tables=0
UNET Froude Limit=0
UNET Froude Power=0
Write IC File=0
Echo Input=False
Echo Output=False
Write Detailed=0

--- BRUSHYFRK.f01 (steady flow) ---

Flow Title=NFF Regression Equation
Program Version=4.00
Number of Profiles=1
Profile Names=P100yr
River Rch & RM=BRUSHYFRK,Main      ,12452.2
924.2843
River Rch & RM=BRUSHYFRK,Main      ,8437
999.2360
River Rch & RM=BRUSHYFRK,Main      ,8437
1555.668
River Rch & RM=BRUSHYFRK,Main      ,4041.4
1667.950
River Rch & RM=BRUSHYFRK,Main      ,11.4
1821.401
Boundary for River Rch & Prof#=BRUSHYFRK,Main      ,1
Up Type=0
Dn Type=3
Dn Slope=0.010491

--- BRUSHYFRK.g01 (geometry) ---

Geom Title=USGS 10m DEM
Program Version=4.10

River Reach=BRUSHYFRK       ,Main
Reach XY= 30
     1738831.825      299587.886     1738814.452      299835.741
     1738911.741      300237.638     1739000.923      300353.458
     1739200.134      300942.983     1739258.044      301854.489
     1739381.972      302342.092     1739348.384      302554.044
     1739509.374      303225.802       1739350.7      303507.245
     1738541.116      304036.544     1738456.567      304180.161
     1738081.309      304472.028     1737930.743      304843.811
     1738011.817      305084.718     1738183.231      305308.251
     1738350.013      305378.901     1738718.321      305704.356
     1739005.556      306068.032     1739198.976      306193.118
     1739320.587      306428.233     1739090.104      306999.228
     1738511.003      307497.255     1738341.905      307717.313
     1738190.181      308045.085     1738153.436      308479.285
     1738360.368      309160.308      1738292.42      309498.504
     1738063.868      309841.332     1738125.067       309996.42

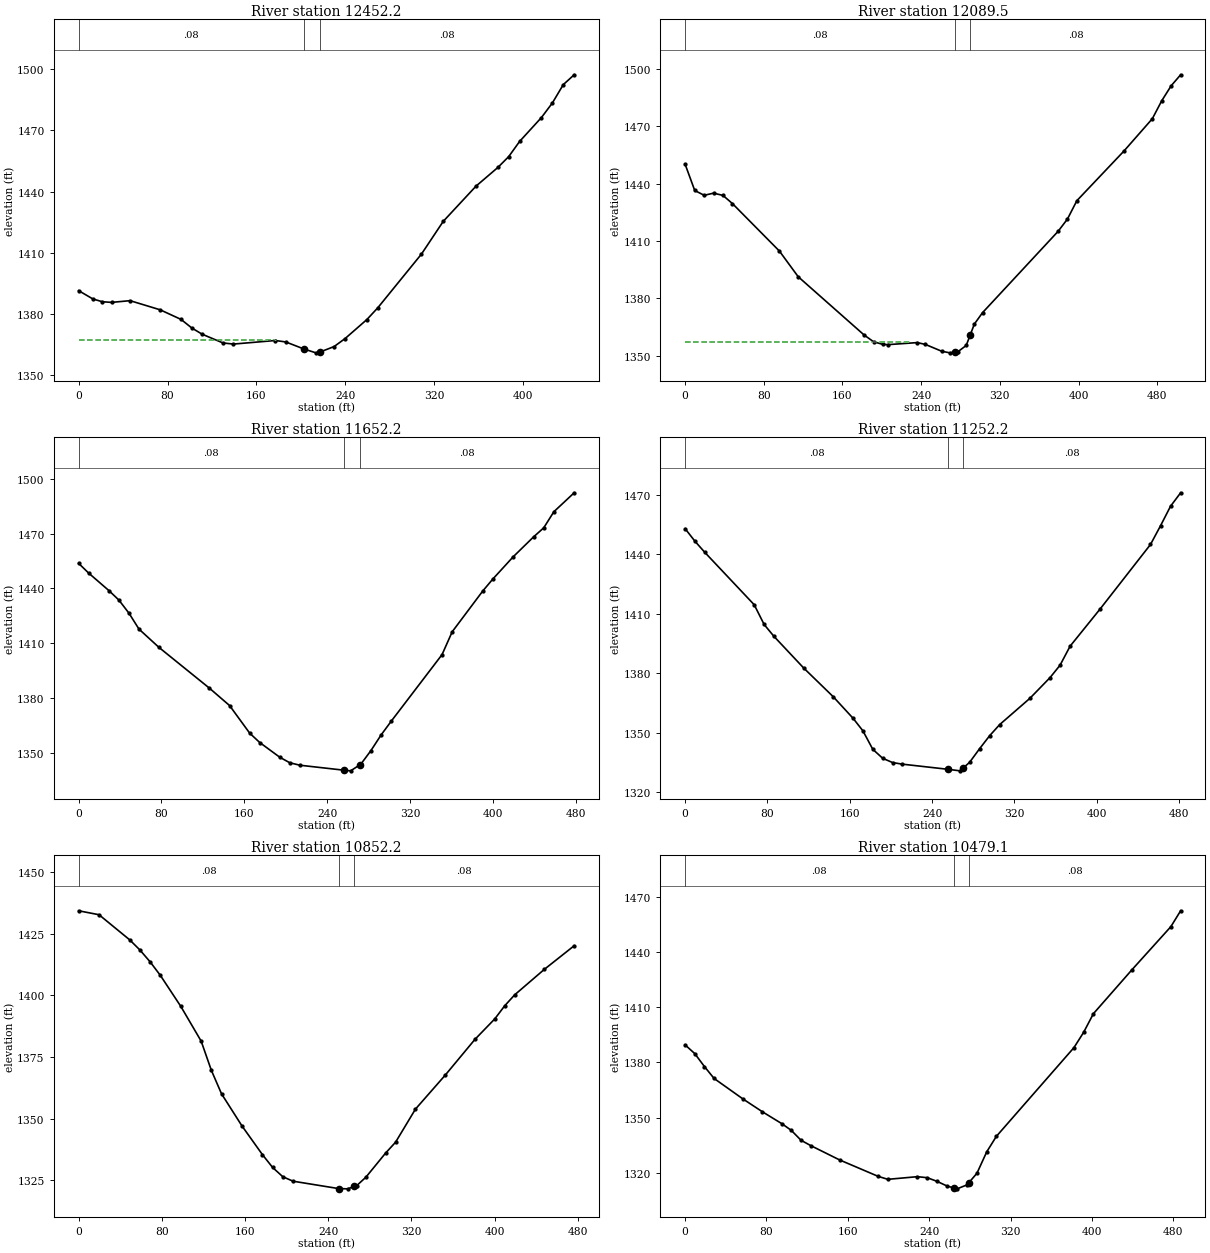
Type RM Length L Ch R = 1 ,12452.2 ,378.9,362.8,346.7
XS GIS Cut Line= 6
     1738639.491      299502.898     1738651.062      299508.683
     1738688.315       299527.31     1738823.066      299594.686
      1738845.15      299605.729     1739038.318      299702.313
#Sta/Elev= 30
       0 1391.49    12.9 1387.41    21.3 1386.07    29.6 1385.75    46.3 1386.59
    73.4 1382.11    92.2  1377.4   101.7 1373.27   111.1 1370.18   129.9 1365.89
   139.3 1365.34     177 1367.09   186.4 1366.38   202.5 1362.98   213.5 1361.05
   217.5 1361.51   229.9 1364.13   239.8 1368.05   259.4 1377.36   269.2 1383.11
   308.5 1409.41   328.1 1425.42   357.6 1442.67   377.2 1451.78     387 1457.12
   396.8 1464.54   416.4 1476.21   426.3 1483.38   436.1 1492.35   445.9 1497.17
#Mann= 3 , 0 , 0
       0     .08       0   202.5    .045       0   217.5     .08       0
#XS Ineff= 2 , 0
          177.59 1367.28
Permanent Ineff=
       F       F
Bank Sta=202.5,217.5
XS Rating Curve= 0 ,0
Exp/Cntr=0.3,0.1

Type RM Length L Ch R = 1 ,12089.5 ,441.6,437.2,432.9
XS GIS Cut Line= 6
     1738574.631      300021.175     1738574.891      300021.108
     1738769.516      299971.447     1738779.437      299968.916
     1738819.363      299958.728     1739062.811      299896.609
#Sta/Elev= 30
       0  1450.1     9.8 1436.35    19.4 1433.84      29 1434.97    38.5 1433.78
    48.1 1429.53    95.9 1404.71     115 1391.31     182 1360.89   191.6 1357.37
   201.1 1355.97   206.2 1355.85   236.1 1356.92   244.3 1355.96   260.9  1352.4
   269.2 1351.57   274.8    1352   277.5  1352.2   285.8 1355.43   289.8  1360.8
   294.1 1366.62   302.4 1372.55   379.2 1415.01   388.7 1421.42   398.3 1431.03
   446.3 1457.03     475 1473.82   484.6 1483.22   494.2 1491.06   503.8 1496.78
#Mann= 3 , 0 , 0
       0     .08       0   274.8    .045       0   289.8     .08       0
#XS Ineff= 2 , 0
          229.05 1357.26
Permanent Ineff=
       F       F
Bank Sta=274.8,289.8
XS Rating Curve= 0 ,0
Exp/Cntr=0.3,0.1

Type RM Length L Ch R = 1 ,11652.2 ,398.2,400,401.8
XS GIS Cut Line= 4
     1738761.259      300465.599     1738945.233      300377.332
     1739006.947      300347.723     1739192.768       300258.57
#Sta/Elev= 30
       0 1453.73     9.7 1448.39    29.2 1438.83    38.9 1433.61    48.6 1426.44
    58.3  1417.7    77.7 1407.63   126.3 1385.36   145.8 1375.82   165.2 1360.71
   174.9 1355.58   194.3  1347.5     204 1344.46   213.8 1343.13   256.4  1340.4
   262.7 1340.06   271.4 1343.26   272.5 1343.67   282.3 1351.14   292.1 1359.69
   301.9 1367.24     351 1403.74   360.8 1416.25   390.3 1438.57   400.1 1445.17
   419.7 1457.32   439.4 1468.23   449.2 1473.19     459 1482.01   478.6 1492.39
#Mann= 3 , 0 , 0
       0     .08       0   256.4    .045       0   271.4     .08       0
Bank Sta=256.4,271.4
XS Rating Curve= 0 ,0
Exp/Cntr=0.3,0.1

Type RM Length L Ch R = 1 ,11252.2 ,393.2,400,406.8
XS GIS Cut Line= 4
     1738866.341      300826.123     1739054.912      300754.907
     1739125.042      300728.422      1739316.89      300655.968
#Sta/Elev= 30
       0 1452.82     9.6 1446.47    19.2 1440.85    67.2 1414.46    76.8 1404.55
    86.4 1398.53   115.2 1382.64     144 1368.13   163.2 1357.31   172.8 1350.97
   182.4 1341.67     192 1337.14   201.6 1334.99   210.9 1334.19   255.2  1331.6
   267.2 1330.81   270.2  1332.2   276.5  1335.1   286.3 1342.02   296.1 1348.58
   305.8 1354.14   335.1 1367.34   354.7 1377.79   364.4 1384.02   374.2 1393.63
   403.5 1412.45   452.3 1444.84   462.1 1454.32   471.8 1464.12   481.6 1470.89
#Mann= 3 , 0 , 0
       0     .08       0   255.2    .045       0   270.2     .08       0
Bank Sta=255.2,270.2
XS Rating Curve= 0 ,0
Exp/Cntr=0.3,0.1

Type RM Length L Ch R = 1 ,10852.2 ,372.8,373.1,373.4
XS GIS Cut Line= 4
      1738936.61      301129.787      1739142.36      301117.326
     1739212.162      301113.098     1739412.192      301100.983
#Sta/Elev= 30
       0 1434.28    19.6 1432.68    49.1  1422.5    58.9  1418.4    68.7  1413.6
    78.5 1408.14    98.2 1395.56   117.8 1381.45   127.6 1369.62   137.4 1360.09
     157 1347.11   176.7 1335.46   186.5 1330.26   196.3  1326.5   206.1  1324.7
     250  1321.7   258.6  1321.6     265 1322.55   267.3  1322.9   276.1 1326.28
   295.1 1336.09   304.7  1340.5   323.8  1353.9   352.4 1367.65     381 1382.17
   400.1 1390.48   409.7 1395.82   419.2 1400.21   447.8 1410.57   476.4 1420.11
#Mann= 3 , 0 , 0
       0     .08       0     250    .045       0     265     .08       0
Bank Sta=250,265
XS Rating Curve= 0 ,0
Exp/Cntr=0.3,0.1

Type RM Length L Ch R = 1 ,10479.1 ,435.3,434.1,432.9
XS GIS Cut Line= 4
     1738984.591      301494.118     1739193.241      301483.878
      1739271.28      301480.048      1739471.28      301470.233
#Sta/Elev= 30
       0 1389.52     9.5 1384.79      19 1377.77    28.5  1371.3      57 1360.13
      76 1353.22      95  1346.8   104.4 1343.15     114 1337.75   123.4  1334.9
   151.9 1327.09   189.9 1318.15   199.4 1316.55   228.4 1317.99   238.2 1317.43
     248 1315.39   257.7 1312.89     264 1311.93   267.5 1311.39   277.3 1313.58
     279 1314.69     287 1319.86   296.6 1331.45   306.1 1339.88   382.4 1388.04
   391.9 1396.32   401.5 1406.44   439.6  1430.4   477.7 1453.69   487.3  1462.3
#Mann= 3 , 0 , 0
       0     .08       0     264    .045       0     279     .08       0
Bank Sta=264,279
XS Rating Curve= 0 ,0
Exp/Cntr=0.3,0.1

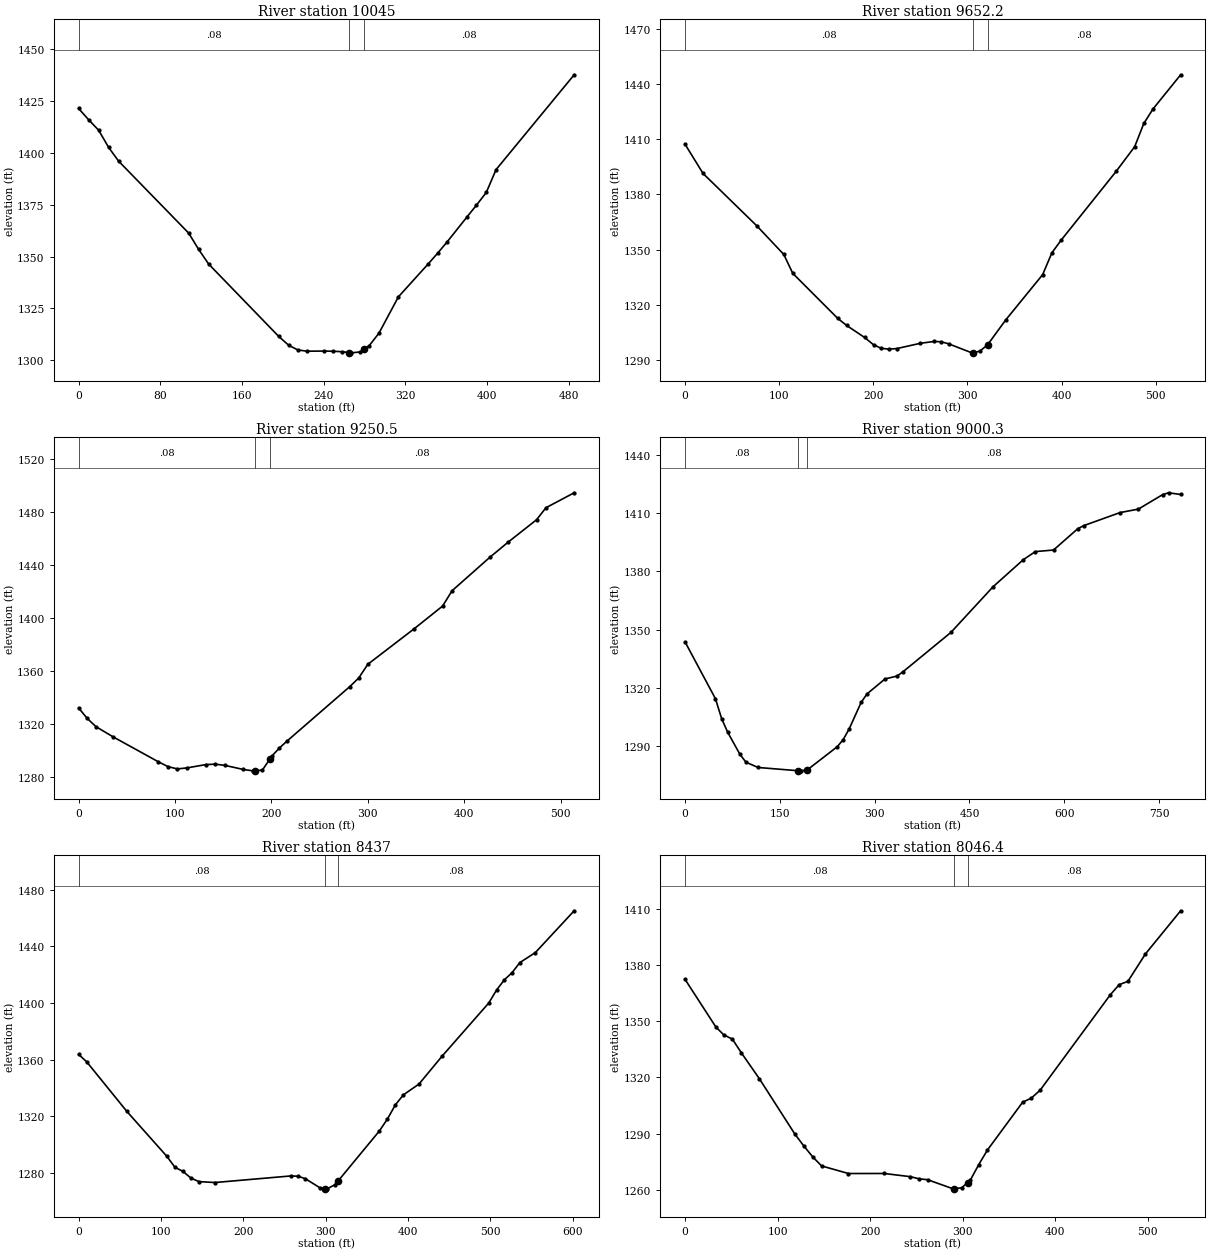
Type RM Length L Ch R = 1 ,10045   ,392.1,392.8,393.5
XS GIS Cut Line= 4
     1739015.268      301935.467     1739219.996      301914.492
     1739298.387       301906.46     1739498.269      301885.981
#Sta/Elev= 30
       0 1421.34     9.8 1415.91    19.6 1410.88    29.4 1402.59    39.2 1395.96
   107.8 1361.33   117.6 1353.46   127.4  1346.4     196 1311.57   205.8 1307.29
   214.6 1305.07   223.3 1304.44   240.8 1304.49   249.6  1304.4   258.3 1304.18
   264.5  1303.8   267.1 1303.64   275.8 1304.07   279.5 1305.31   284.6 1307.04
   294.2 1313.09   313.3 1330.62     342  1346.2   351.6 1351.56   361.2 1357.17
   380.3 1368.99   389.8 1374.79   399.4  1380.9     409 1391.92   485.5 1437.58
#Mann= 3 , 0 , 0
       0     .08       0   264.5    .045       0   279.5     .08       0
Bank Sta=264.5,279.5
XS Rating Curve= 0 ,0
Exp/Cntr=0.3,0.1

Type RM Length L Ch R = 1 ,9652.2  ,402.4,401.8,401.2
XS GIS Cut Line= 6
     1739061.561      302307.605     1739261.324      302294.228
     1739310.774      302290.917     1739340.814      302288.906
       1739382.1      302286.141     1739586.924      302272.426
#Sta/Elev= 30
       0 1407.17    19.1 1391.32    76.3 1362.81   104.9 1347.29   114.4 1337.04
   162.1 1312.61   171.6 1308.73   190.7  1302.2   200.2 1298.23   208.5 1296.28
   216.7 1295.85     225 1296.17   249.8 1299.01   264.8 1300.05   272.4 1299.81
   279.9 1298.76   304.7 1293.84   306.3    1294     313  1294.7   321.3 1298.13
   321.3 1298.16   340.8 1311.82   379.9 1336.35   389.7  1348.2   399.5 1355.06
   458.1 1392.54   477.7 1405.92   487.4 1418.55   497.2 1426.42   526.5 1444.97
#Mann= 3 , 0 , 0
       0     .08       0   306.3    .045       0   321.3     .08       0
Bank Sta=306.3,321.3
XS Rating Curve= 0 ,0
Exp/Cntr=0.3,0.1

Type RM Length L Ch R = 1 ,9250.5  ,254.9,250.2,245.4
XS GIS Cut Line= 6
     1739192.785         302695.     1739255.743       302689.65
     1739431.751      302674.695     1739454.307      302672.778
     1739501.029      302668.808     1739705.036      302651.474
#Sta/Elev= 30
       0 1331.76       9 1323.85      18 1317.67    36.1 1309.85    82.8 1291.14
    92.6 1287.56   102.4  1285.8   112.2 1286.55   131.8 1289.04   141.6 1289.39
   151.4 1288.52     171 1285.37   180.8 1284.35   183.1 1284.47   190.6 1284.89
   198.1 1292.92   200.4 1295.46   208.3 1301.56   216.2 1306.83   281.2 1347.82
   290.6  1354.4     300 1364.73   348.4 1391.72   377.6 1408.67   387.4 1420.22
   426.4 1445.34   445.8 1457.02   475.1 1473.82   484.8 1482.85   514.1 1494.15
#Mann= 3 , 0 , 0
       0     .08       0   183.1    .045       0   198.1     .08       0
Bank Sta=183.1,198.1
XS Rating Curve= 0 ,0
Exp/Cntr=0.3,0.1

Type RM Length L Ch R = 1 ,9000.3  ,541.3,563.3,585.4
XS GIS Cut Line= 4
     1739265.992       302974.95     1739496.222      302904.823
     1739713.677      302838.587     1740016.081      302746.476
#Sta/Elev= 30
       0 1343.65    48.1  1314.4    57.8 1304.21    67.4 1297.19    86.6 1285.92
    96.3 1281.77   115.5 1279.07   178.2 1277.41   182.9 1277.34   193.2  1277.8
   240.7 1289.73   250.2 1293.44   259.6  1298.9   278.6 1312.59     288 1316.97
   316.4 1324.64   335.4 1326.11   344.9 1328.35   420.6 1348.57   487.2 1372.04
     535 1385.96   554.2 1390.16     583 1390.97   621.3 1401.93   630.8 1403.53
   688.3 1410.25   717.1 1412.01   755.4 1419.44     765 1420.43   784.1 1419.55
#Mann= 3 , 0 , 0
       0     .08       0   178.2    .045       0   193.2     .08       0
Bank Sta=178.2,193.2
XS Rating Curve= 0 ,0
Exp/Cntr=0.3,0.1

Type RM Length L Ch R = 1 ,8437    ,385.8,390.6,395.3
XS GIS Cut Line= 6
     1739173.149      303253.285     1739339.653      303388.394
     1739393.683      303432.237     1739449.278       303477.35
     1739479.431      303501.817     1739640.491       303632.51
#Sta/Elev= 30
       0 1363.68     9.8 1358.44    58.5 1323.46   107.2 1291.64     117 1283.93
   126.7 1281.03   136.4 1276.32   146.2  1273.8   165.7 1273.19   257.9 1277.84
   266.6 1277.61   275.3 1275.89     293 1269.46   299.8 1268.89   301.9 1268.72
   310.8 1271.52   314.8 1274.08   365.3 1309.64     375 1318.05   384.7 1328.08
   394.4 1335.11   413.3 1342.72   441.6 1362.59   498.1 1400.01   507.6 1409.18
     517 1416.37   526.4 1421.42   535.8 1428.54   554.7 1435.64   601.8 1465.14
#Mann= 3 , 0 , 0
       0     .08       0   299.8    .045       0   314.8     .08       0
#XS Ineff= 2 , 0
          260.41  1277.6
Permanent Ineff=
       F       F
Bank Sta=299.8,314.8
XS Rating Curve= 0 ,0
Exp/Cntr=0.3,0.1

Type RM Length L Ch R = 1 ,8046.4  ,391.7,394.1,396.6
XS GIS Cut Line= 5
     1738904.714      303434.486     1738930.784      303466.883
     1739051.675      303617.109     1739103.675      303681.728
     1739240.487      303851.739
#Sta/Elev= 30
       0 1372.26    33.3 1346.89    41.6 1342.81    51.2 1340.39    60.9 1333.07
    80.2 1319.39   118.7 1289.77   128.4 1283.42     138 1277.63   147.6 1272.81
   176.6 1268.78   215.1  1268.8   243.6 1267.09   252.8 1265.96   262.1 1265.49
   289.7 1260.61   290.3 1260.65   298.9 1261.17   305.3 1263.88   308.1 1265.08
   317.4 1273.55   326.8 1281.32   364.8 1306.78   374.3 1309.03   383.8 1313.26
   459.7 1364.18   469.2  1369.5   478.6 1371.25   497.6 1385.91   535.6 1408.89
#Mann= 3 , 0 , 0
       0     .08       0   290.3    .045       0   305.3     .08       0
Bank Sta=290.3,305.3
XS Rating Curve= 0 ,0
Exp/Cntr=0.3,0.1

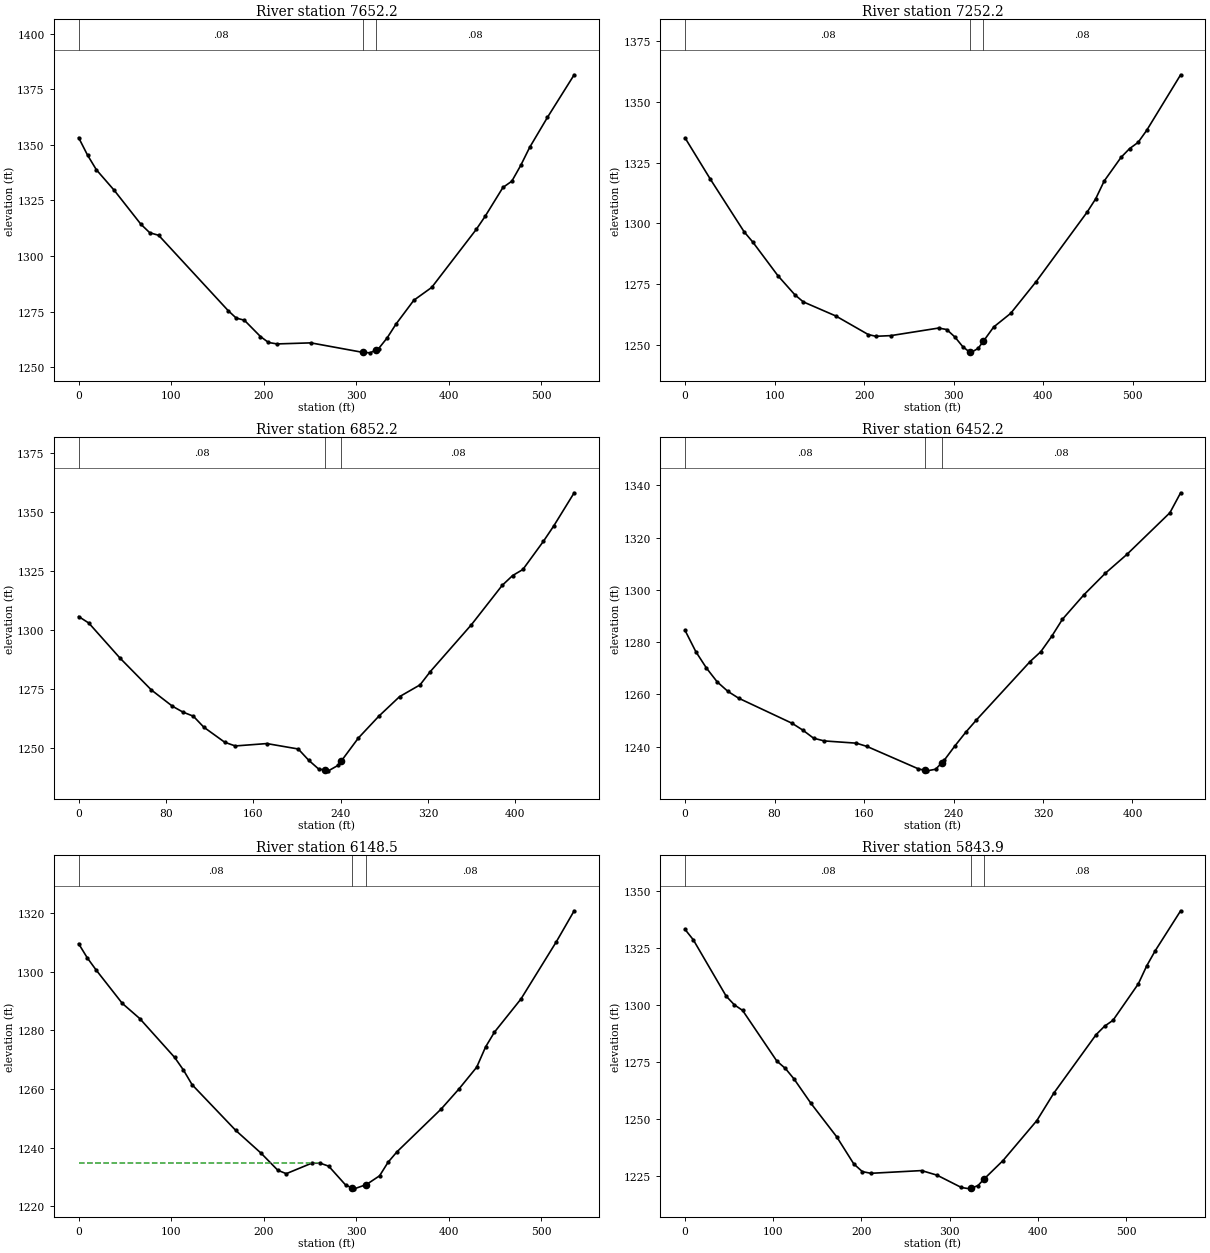
Type RM Length L Ch R = 1 ,7652.2  ,407.6,400,392.4
XS GIS Cut Line= 5
     1738601.322      303626.579      1738678.58      303748.295
     1738711.307      303799.855     1738780.011      303908.094
     1738888.352       304078.78
#Sta/Elev= 30
       0 1353.25     9.6 1345.41    19.2 1338.78    38.4 1329.59    67.3 1314.28
    76.9 1310.45    86.5  1309.3   161.6 1275.41   170.3 1272.05   179.1 1271.09
   196.5 1263.75   205.2 1261.07   214.4 1260.41     251 1260.89   306.9 1256.63
   315.1  1256.4   321.9 1257.84   324.3 1258.35   333.4 1263.09   343.1 1269.39
   362.3 1280.07   381.6 1285.84   429.7 1311.92   439.3  1317.8   458.6 1330.83
   468.2 1333.65   477.8 1340.73   487.5 1348.88   506.7 1362.37   535.6 1381.55
#Mann= 3 , 0 , 0
       0     .08       0   306.9    .045       0   321.9     .08       0
Bank Sta=306.9,321.9
XS Rating Curve= 0 ,0
Exp/Cntr=0.3,0.1

Type RM Length L Ch R = 1 ,7252.2  ,393.3,400,406.7
XS GIS Cut Line= 6
     1738222.486      303943.835     1738327.546      304023.789
     1738385.242      304067.698     1738418.761      304093.208
     1738496.728      304152.543     1738662.829      304278.953
#Sta/Elev= 30
       0 1335.12    28.3 1318.12      66  1296.5    75.4 1292.42   103.7 1278.47
   122.6 1270.64     132 1267.73   168.3 1261.94   204.5 1254.31     213 1253.58
   229.8 1253.86   283.1 1256.97   292.2 1256.36   301.4 1253.25     310 1249.36
   318.1 1246.95   318.7 1246.78   327.3 1248.63   333.1 1251.54   344.6  1257.4
   363.6 1263.01   392.1 1276.09     449 1304.65   458.5 1310.09     468 1317.41
   486.9 1327.17   496.4 1330.75   505.9  1333.3   515.4  1338.2   553.4  1361.1
#Mann= 3 , 0 , 0
       0     .08       0   318.1    .045       0   333.1     .08       0
#XS Ineff= 2 , 0
          283.79 1256.88
Permanent Ineff=
       F       F
Bank Sta=318.1,333.1
XS Rating Curve= 0 ,0
Exp/Cntr=0.3,0.1

Type RM Length L Ch R = 1 ,6852.2  ,411,400,389
XS GIS Cut Line= 5
     1738052.745      304215.796     1738063.535      304230.988
     1738174.803      304387.639     1738195.712      304417.076
     1738315.676      304585.971
#Sta/Elev= 30
       0 1305.72     9.3 1302.97    37.8 1288.16    66.7 1274.57    85.9 1267.72
    95.5 1265.23   105.1 1263.48   114.7 1258.82   133.9 1252.42   143.5 1250.87
   172.4 1251.88   201.2 1249.58   210.8  1244.8   219.8 1241.13   225.7  1240.6
   228.8 1240.32   237.9  1242.7   240.7 1244.52   256.3 1254.24   275.1 1263.51
     294 1271.76   312.8 1276.76   322.2 1282.39   359.9 1302.28   388.1 1318.95
   397.6 1323.08     407 1325.66   425.8 1337.59   435.2 1344.05     454 1358.17
#Mann= 3 , 0 , 0
       0     .08       0   225.7    .045       0   240.7     .08       0
Bank Sta=225.7,240.7
XS Rating Curve= 0 ,0
Exp/Cntr=0.3,0.1

Type RM Length L Ch R = 1 ,6452.2  ,327,303.8,280.6
XS GIS Cut Line= 4
     1737776.352       304622.34      1737955.45      304713.624
     1737982.726      304727.527     1738171.111      304823.545
#Sta/Elev= 30
       0 1284.46     9.6 1276.36    19.1 1270.08    28.7  1264.8    38.3 1261.16
    47.9 1258.56    95.7 1248.96   105.3 1246.34   114.9 1243.26   124.4 1242.22
   153.2 1241.36   162.7  1240.1   208.7 1231.52   214.7 1230.93   216.3 1230.78
     224 1231.39   229.7 1233.92   231.6 1234.77   241.2 1240.28   250.9 1245.52
   260.5 1250.24   308.5 1272.58   318.1 1276.36   327.8 1282.21   337.4 1288.74
   356.6  1298.1   375.8 1306.36     395 1313.53   433.5 1329.48   443.1 1337.12
#Mann= 3 , 0 , 0
       0     .08       0   214.7    .045       0   229.7     .08       0
Bank Sta=214.7,229.7
XS Rating Curve= 0 ,0
Exp/Cntr=0.3,0.1

Type RM Length L Ch R = 1 ,6148.5  ,307,304.5,302.1
XS GIS Cut Line= 5
     1737717.329      305171.065     1737861.634       305081.33
     1737892.416      305062.188     1738001.475      304994.371
     1738172.292       304888.15
#Sta/Elev= 30
       0 1309.59     9.4 1304.74    18.9 1300.63    47.2 1289.24    66.1 1284.06
   103.8 1270.81   113.3 1266.52   122.7  1261.5   169.9 1245.91   197.1  1238.2
   215.4 1232.32   224.5 1231.16     252 1234.74   261.2 1234.74   270.4 1233.72
   288.7 1227.29   296.1 1226.24   297.9 1225.99   311.1 1227.44   325.4 1230.44
   334.6 1235.07   344.2 1238.62   392.1 1253.25   411.2 1260.04   430.4 1267.47
     440 1274.37   449.6 1279.43   478.3 1290.75   516.6  1310.3   535.8 1320.82
#Mann= 3 , 0 , 0
       0     .08       0   296.1    .045       0   311.1     .08       0
#XS Ineff= 2 , 0
          260.41 1234.77
Permanent Ineff=
       F       F
Bank Sta=296.1,311.1
XS Rating Curve= 0 ,0
Exp/Cntr=0.3,0.1

Type RM Length L Ch R = 1 ,5843.9  ,262.5,254.7,247
XS GIS Cut Line= 6
     1737884.917      305465.692     1738050.799      305335.748
     1738096.035      305300.312      1738116.72      305284.108
     1738168.734      305243.363     1738327.231      305119.204
#Sta/Elev= 30
       0 1333.21     9.3 1328.68    46.6 1303.89    55.9 1300.07    65.2 1297.63
     104 1275.37   113.7 1272.11   123.4 1267.55   142.8 1256.72   171.9 1242.05
   191.3 1230.12     201 1226.74   210.7    1226   268.2  1227.2   285.7 1225.18
   313.3 1219.76   322.8 1219.17   323.8 1219.33   332.2 1220.63   338.8 1223.41
   360.5 1231.61   398.9 1249.21   418.1 1261.26     466 1286.95   475.6 1290.67
   485.2 1293.28   513.9  1309.3   523.5 1317.27   533.1 1323.88   561.9 1341.44
#Mann= 3 , 0 , 0
       0     .08       0   323.8    .045       0   338.8     .08       0
Bank Sta=323.8,338.8
XS Rating Curve= 0 ,0
Exp/Cntr=0.3,0.1

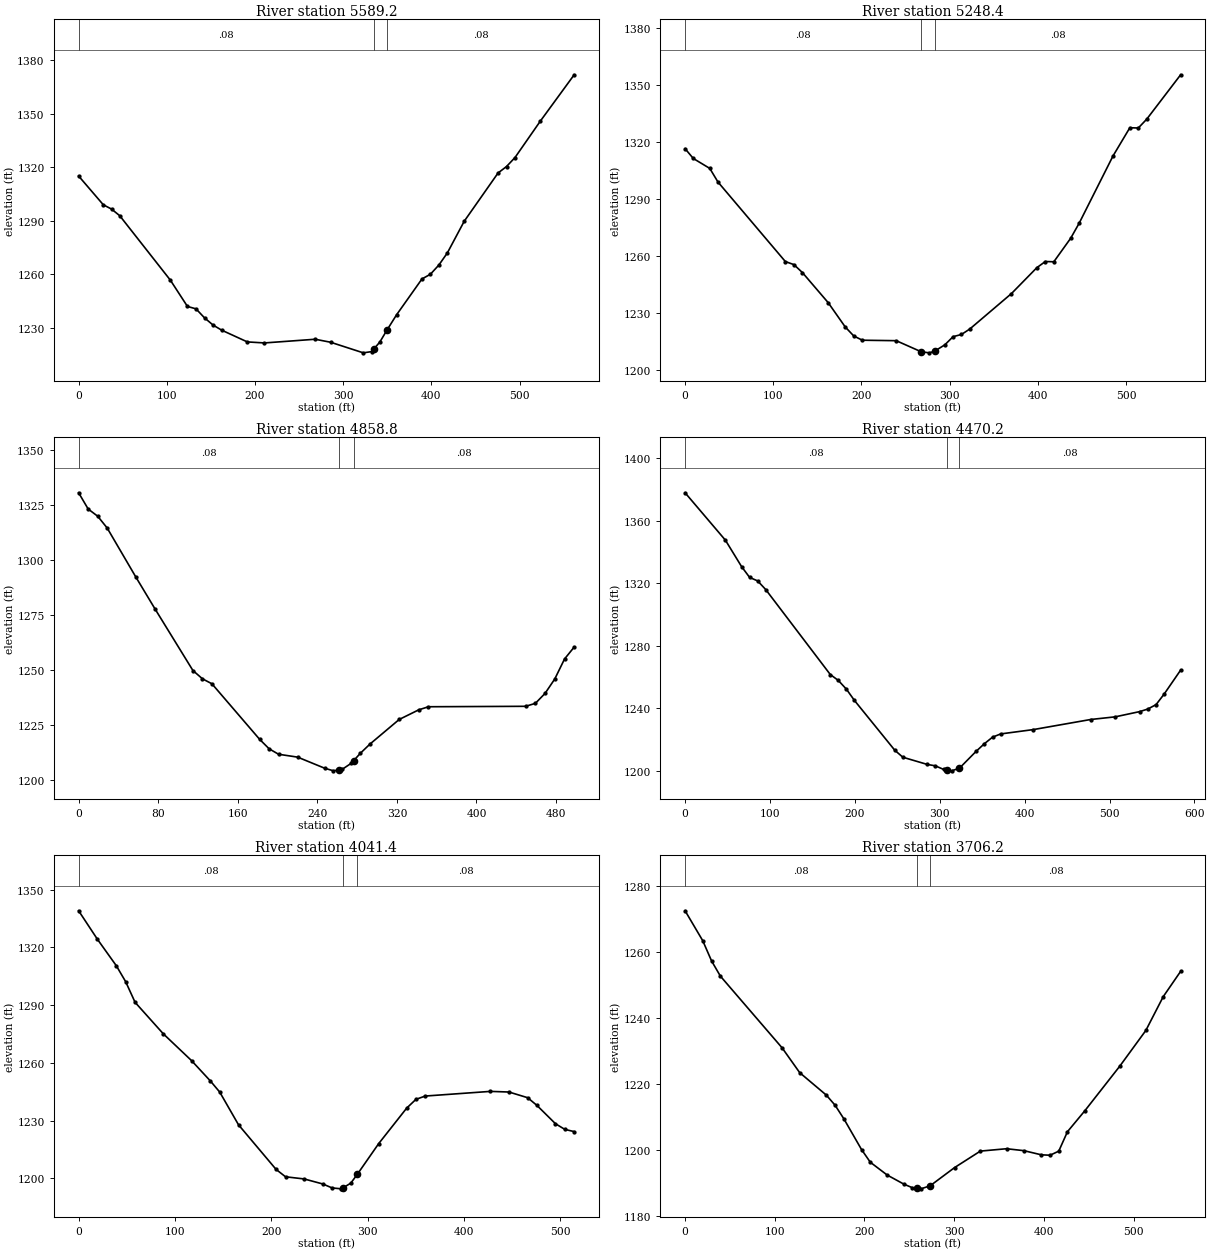
Type RM Length L Ch R = 1 ,5589.2  ,338.1,340.8,343.5
XS GIS Cut Line= 6
     1738175.006      305674.238     1738287.283      305495.924
     1738317.901      305447.297     1738331.902      305425.062
     1738367.108       305369.15     1738474.387      305198.774
#Sta/Elev= 30
       0  1315.1      28 1298.95    37.3 1296.56    46.6 1292.83     104 1256.66
   123.4 1241.89   133.1 1240.54   142.8 1235.46   152.5 1231.42   162.2 1228.58
   191.3 1221.98   210.7 1221.41   268.2 1223.48   285.7  1221.8   322.8 1215.85
   332.2 1216.54   334.7 1217.97   341.6 1221.96   349.7 1228.68   360.5 1237.19
   389.3 1257.32   398.9 1259.98   408.5 1265.15   418.1 1271.94   437.2  1289.7
   475.6 1316.81   485.2 1320.45   494.8 1325.48   523.5 1345.91   561.9 1371.94
#Mann= 3 , 0 , 0
       0     .08       0   334.7    .045       0   349.7     .08       0
Bank Sta=334.7,349.7
XS Rating Curve= 0 ,0
Exp/Cntr=0.3,0.1

Type RM Length L Ch R = 1 ,5248.4  ,387.4,389.6,391.8
XS GIS Cut Line= 6
     1738424.642      305835.442     1738465.762      305784.775
     1738557.427      305671.826     1738593.638      305627.208
     1738610.196      305606.805     1738778.706      305399.169
#Sta/Elev= 30
       0 1316.63     9.3 1311.48      28 1306.24    37.3 1299.06   113.7 1257.18
   123.4 1255.58   133.1 1251.35   162.2 1235.57   181.6 1222.73   191.3 1217.98
     201 1215.76   239.4 1215.51   267.8 1209.66   276.9 1209.11   282.8 1209.95
   294.5 1213.32   303.9 1217.64   313.3 1218.77   322.8 1221.65   370.1 1240.34
   398.9 1253.99   408.5 1257.21   418.1 1257.07   437.2 1269.45   446.8 1277.35
   485.2 1312.79   504.3 1327.67   513.9 1327.53   523.5 1332.21   561.9 1355.56
#Mann= 3 , 0 , 0
       0     .08       0   267.8    .045       0   282.8     .08       0
Bank Sta=267.8,282.8
XS Rating Curve= 0 ,0
Exp/Cntr=0.3,0.1

Type RM Length L Ch R = 1 ,4858.8  ,389,388.6,388.1
XS GIS Cut Line= 4
     1738671.778      306089.057     1738824.906      305930.818
     1738868.751      305885.509     1739018.263      305731.006
#Sta/Elev= 30
       0 1330.36     9.6 1322.97    19.2 1319.69    28.7 1314.34    57.4 1292.14
    76.6  1277.7   114.9 1249.55   124.5 1245.78     134 1243.52   181.9  1218.3
   191.5 1213.97     201 1211.48   220.2 1210.17   247.2 1205.16   256.2 1203.94
   261.4 1204.37   265.2 1204.69   274.2 1207.42   276.4  1208.5   283.2 1211.91
     293 1216.15   322.3  1227.3   341.9 1231.67   351.7 1233.08   449.4 1233.28
   459.2 1234.62   468.9 1239.14   478.7 1245.71   488.5 1254.78   498.2 1260.21
#Mann= 3 , 0 , 0
       0     .08       0   261.4    .045       0   276.4     .08       0
Bank Sta=261.4,276.4
XS Rating Curve= 0 ,0
Exp/Cntr=0.3,0.1

Type RM Length L Ch R = 1 ,4470.2  ,402.1,428.8,455.6
XS GIS Cut Line= 4
     1738926.591      306386.294     1739107.481       306191.21
      1739166.24      306127.841     1739323.447      305958.299
#Sta/Elev= 30
       0 1377.84    47.5 1347.47    66.5  1330.6      76 1323.66    85.5  1321.4
      95 1315.86     171 1261.49   180.5 1257.68     190  1252.1   199.5 1244.86
     247 1212.99   256.5 1208.52   285.2 1203.92   294.8 1203.01   304.4 1200.73
   308.2 1200.37     314 1199.81   323.2 1201.53   342.9 1212.36   352.5 1217.17
   362.1 1221.36   371.7 1223.44   410.3 1226.23   477.7 1232.68   506.6 1234.38
   535.5 1237.74   545.1 1239.39   554.8 1242.23   564.4 1249.06   583.7  1264.3
#Mann= 3 , 0 , 0
       0     .08       0   308.2    .045       0   323.2     .08       0
Bank Sta=308.2,323.2
XS Rating Curve= 0 ,0
Exp/Cntr=0.3,0.1

Type RM Length L Ch R = 1 ,4041.4  ,338.2,335.2,332.1
XS GIS Cut Line= 4
     1739024.618      306410.626     1739225.591      306486.499
     1739298.049      306513.854     1739505.924      306592.332
#Sta/Elev= 30
       0 1339.07    19.5 1324.26    39.1 1310.52    48.8 1302.23    58.6 1291.48
    87.9  1275.1   117.2 1261.18   136.7 1250.63   146.5  1244.8     166 1227.79
     205  1204.6   214.8 1200.76   234.2 1199.63   253.5 1197.02   263.2 1194.96
   272.9 1194.49   274.5 1194.98   282.6 1197.47   289.5 1202.15   311.6 1218.05
   340.6 1236.46   350.2 1241.02   359.9 1242.74   427.5 1245.16   446.8 1244.83
   466.2 1241.88   475.8 1237.89   495.1 1228.34   504.8  1225.4   514.5 1224.25
#Mann= 3 , 0 , 0
       0     .08       0   274.5    .045       0   289.5     .08       0
Bank Sta=274.5,289.5
XS Rating Curve= 0 ,0
Exp/Cntr=0.3,0.1

Type RM Length L Ch R = 1 ,3706.2  ,447.3,460.7,474.1
XS GIS Cut Line= 4
     1738887.466      306751.563     1739088.856      306797.331
     1739189.599      306820.225     1739426.233      306874.003
#Sta/Elev= 30
       0 1272.62    19.7 1263.53    29.5 1257.41    39.3 1252.81   108.2 1231.02
   127.8  1223.5   157.4 1216.71   167.2 1213.64     177 1209.51   196.7 1200.19
   206.5 1196.33   225.3 1192.45   244.1 1189.66   253.5 1188.59   258.2 1188.43
   262.9 1188.26   273.2 1189.18   300.4  1194.7   329.2 1199.71   358.4 1200.43
   377.8 1199.84   397.2 1198.58   406.9 1198.46   416.6 1199.69   426.3 1205.59
   445.7 1211.95   484.6 1225.46   513.7 1236.31   533.1 1246.57   552.5 1254.24
#Mann= 3 , 0 , 0
       0     .08       0   258.2    .045       0   273.2     .08       0
Bank Sta=258.2,273.2
XS Rating Curve= 0 ,0
Exp/Cntr=0.3,0.1

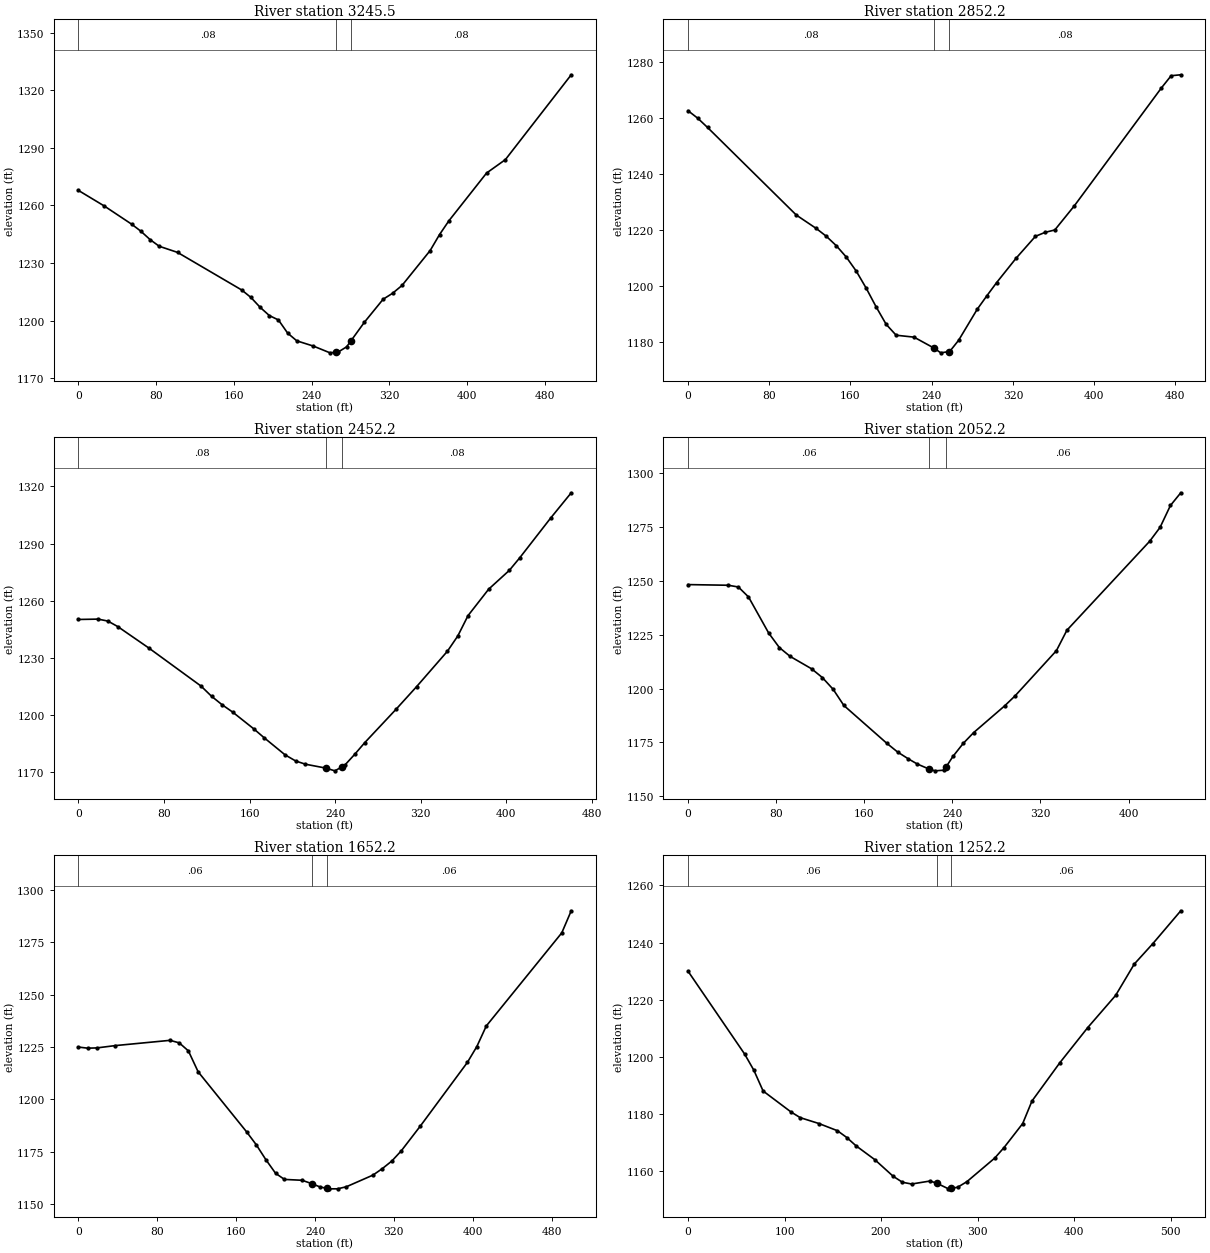
Type RM Length L Ch R = 1 ,3245.5  ,394.6,393.3,392.1
XS GIS Cut Line= 5
     1738700.543      306964.911     1738712.223      306977.268
     1738854.973      307128.288     1738896.105      307171.803
     1739049.052      307333.612
#Sta/Elev= 30
       0 1267.77    26.4 1259.73    54.8 1250.19    64.2 1246.56    73.7  1242.2
    83.1 1238.72     102 1235.52   168.1 1215.93   177.6 1212.04     187 1206.94
   196.5 1202.63   205.9 1200.33   215.4 1193.47   224.8 1189.46   241.9 1186.72
     259 1183.21   265.6 1183.58   267.6 1183.69   276.1 1186.34   280.6 1189.49
   294.4 1199.14   313.7 1211.13   323.4 1214.22   333.1 1218.28   362.1 1236.47
   371.8 1244.82   381.5 1252.03   420.2 1276.84   439.6 1283.84   507.4 1328.02
#Mann= 3 , 0 , 0
       0     .08       0   265.6    .045       0   280.6     .08       0
Bank Sta=265.6,280.6
XS Rating Curve= 0 ,0
Exp/Cntr=0.3,0.1

Type RM Length L Ch R = 1 ,2852.2  ,406,400,394
XS GIS Cut Line= 5
     1738413.615      307251.728     1738455.352      307291.273
      1738562.42      307392.719     1738613.515      307441.131
     1738766.009      307585.617
#Sta/Elev= 30
       0  1262.6     9.6  1259.9    19.2 1256.62   106.7 1225.29   126.3 1220.51
   136.2 1217.72     146 1214.37   155.8 1210.33   165.7 1205.27   175.5 1199.17
   185.3 1192.48   195.2 1186.23     205 1182.35   222.6 1181.66   241.9 1177.83
     249 1176.05   256.9 1176.49   257.8 1176.54   266.6 1180.56   284.9 1191.64
   294.5  1196.5     304 1201.16   323.1 1209.84   342.2 1217.69   351.8 1219.12
   361.3 1219.97   380.4 1228.53   466.4 1270.78   475.9  1275.1   485.4 1275.44
#Mann= 3 , 0 , 0
       0     .08       0   241.9    .045       0   256.9     .08       0
Bank Sta=241.9,256.9
XS Rating Curve= 0 ,0
Exp/Cntr=0.3,0.1

Type RM Length L Ch R = 1 ,2452.2  ,404.6,400,395.4
XS GIS Cut Line= 5
     1738127.419      307613.431     1738167.841      307635.037
     1738306.506      307709.155     1738355.095      307735.126
     1738533.826       307830.66
#Sta/Elev= 30
       0 1250.22    18.3 1250.41    27.5 1249.38    36.7  1246.5    65.5 1235.36
   114.6 1215.29   124.4 1209.96   134.3  1205.5   144.1 1201.68   163.8 1192.91
   173.6  1188.2   193.2 1179.22   203.1 1176.01   212.2 1174.32   231.2 1172.29
   239.8 1170.84   246.2  1172.9     249  1173.8   258.2 1179.43   267.8 1185.69
   296.8 1203.02   316.1 1214.94     345 1233.56   354.7 1241.56   364.3 1252.25
   383.6 1266.12   402.9 1275.97   412.6 1282.53   441.5 1303.37   460.8 1316.66
#Mann= 3 , 0 , 0
       0     .08       0   231.2    .045       0   246.2     .08       0
Bank Sta=231.2,246.2
XS Rating Curve= 0 ,0
Exp/Cntr=0.3,0.1

Type RM Length L Ch R = 1 ,2052.2  ,410.1,400,389.9
XS GIS Cut Line= 5
     1737959.293      308024.789     1738029.471      308045.438
     1738151.285       308081.28     1738190.001      308092.671
     1738388.511       308151.08
#Sta/Elev= 30
       0 1248.34    36.6 1248.03    45.7 1247.22    54.9 1242.61    73.2 1225.85
    82.9 1219.09    92.7 1214.98   112.2 1209.21     122 1205.13   131.8 1199.66
   141.5 1192.17   180.6 1174.55   190.4  1170.5   200.1 1167.35   208.2 1164.96
   219.1 1162.57   224.3  1161.8   232.4 1162.11   234.1 1163.44   240.5 1168.48
   249.9 1174.57   259.3 1179.55   287.5    1192   296.9 1196.61   334.5 1217.65
     344 1227.13   419.2  1268.5   428.6 1274.93     438 1285.09   447.4    1291
#Mann= 3 , 0 , 0
       0     .06       0   219.1    .045       0   234.1     .06       0
Bank Sta=219.1,234.1
XS Rating Curve= 0 ,0
Exp/Cntr=0.3,0.1

Type RM Length L Ch R = 1 ,1652.2  ,400.8,400,399.2
XS GIS Cut Line= 5
     1737913.585      308525.286     1738023.627      308507.118
     1738110.895       308492.71     1738208.395      308476.613
     1738406.898      308443.839
#Sta/Elev= 30
       0 1224.96     9.3 1224.44    18.6 1224.56    37.2 1225.66    92.9 1228.18
   102.2 1226.98   111.5 1223.15   121.4 1213.16   170.5 1184.52   180.3 1178.36
   190.2 1171.13     200 1164.66     209 1161.74   226.9 1161.33   236.9 1159.69
   244.9 1158.18   251.9 1157.45   253.9 1157.24   262.9 1157.25   271.8 1158.23
   298.8  1163.8   308.4 1166.93     318 1170.55   327.5 1175.37   346.7 1187.12
   394.6 1217.63   404.2  1225.2   413.8 1235.04   490.4 1279.52     500 1290.07
#Mann= 3 , 0 , 0
       0     .06       0   236.9    .045       0   251.9     .06       0
Bank Sta=236.9,251.9
XS Rating Curve= 0 ,0
Exp/Cntr=0.3,0.1

Type RM Length L Ch R = 1 ,1252.2  ,393.5,400,406.5
XS GIS Cut Line= 5
     1737998.772      308923.509     1738018.407      308919.522
     1738207.132      308881.193     1738291.349       308864.09
     1738499.177      308821.882
#Sta/Elev= 30
       0 1229.98    58.6 1200.98    68.2 1195.29    77.8 1188.01   106.7 1180.67
   116.3 1178.67   135.6 1176.62   154.8  1174.1   164.5 1171.72   174.1 1168.81
   193.4    1164   212.6 1158.13   222.2 1156.04   231.7 1155.43   250.8 1156.48
   257.9 1155.69   269.9 1153.74   272.9 1153.91   279.4  1154.3     289 1156.26
   317.8 1164.51   327.5 1168.22   346.8 1176.62   356.4  1184.5   385.3 1197.92
   414.2 1210.23   443.1  1221.5   462.4 1232.47   481.7 1239.65   510.6 1251.14
#Mann= 3 , 0 , 0
       0     .06       0   257.9    .045       0   272.9     .06       0
Bank Sta=257.9,272.9
XS Rating Curve= 0 ,0
Exp/Cntr=0.3,0.1

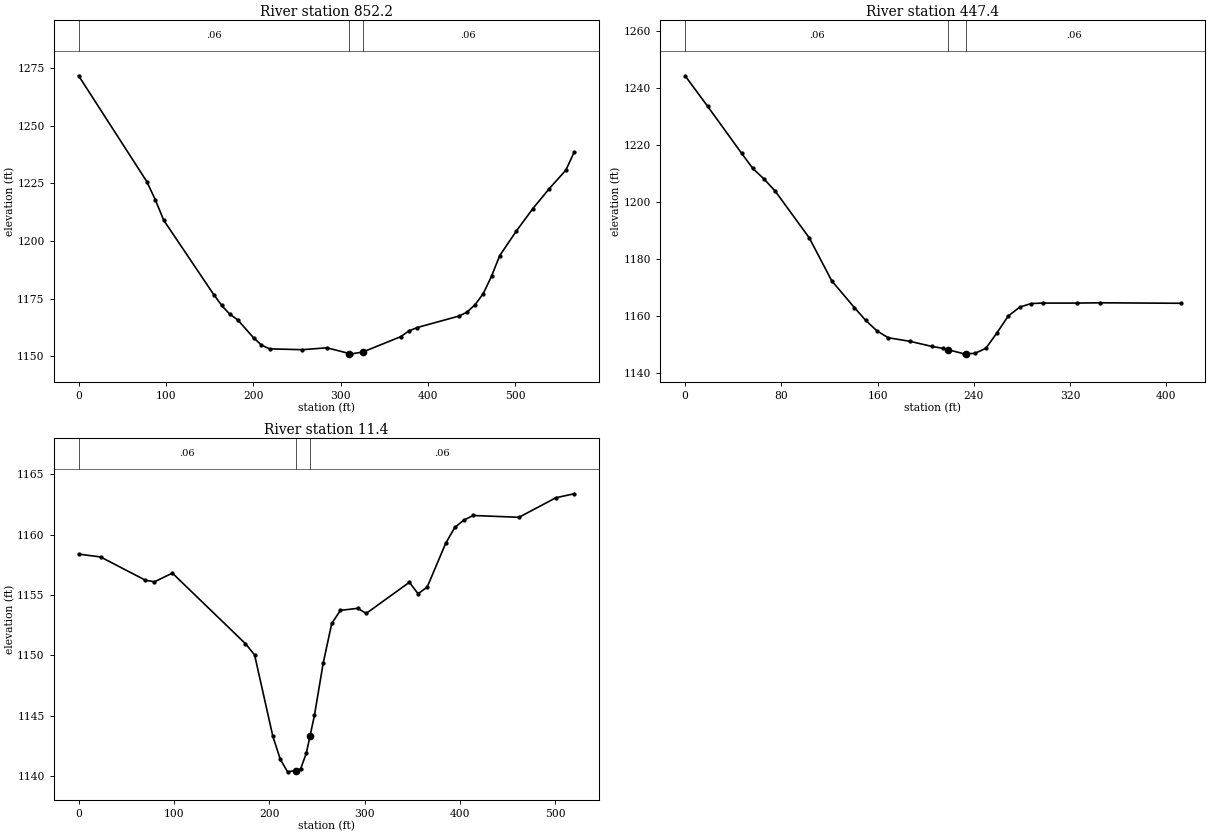
Type RM Length L Ch R = 1 ,852.2   ,391.9,404.9,417.8
XS GIS Cut Line= 5
     1738009.572      309214.556     1738145.605      309225.421
     1738218.201      309231.219     1738367.546      309243.147
     1738574.938      309259.712
#Sta/Elev= 30
       0 1271.68      78 1225.83    87.7 1217.96    97.5 1208.99   154.7 1176.79
   163.8  1172.1   172.9 1168.36     182  1165.9   200.2  1158.1   209.3 1154.92
   218.7 1153.29   256.1 1152.93   284.2 1153.75     310 1151.25   312.3 1151.13
     325 1151.88   368.6 1158.56     378 1161.05   387.5 1162.53   434.8 1167.45
   444.2  1169.1   453.7 1172.41   463.1 1177.21   472.6 1184.77     482 1193.75
     501 1204.35   519.9  1214.1   538.8  1222.8   557.7 1230.77   567.2 1238.57
#Mann= 3 , 0 , 0
       0     .06       0     310    .045       0     325     .06       0
Bank Sta=310,325
XS Rating Curve= 0 ,0
Exp/Cntr=0.3,0.1

Type RM Length L Ch R = 1 ,447.4   ,463.6,435.9,408.3
XS GIS Cut Line= 4
     1738037.811      309482.993     1738172.115      309585.324
     1738243.869      309639.996     1738365.443      309732.628
#Sta/Elev= 28
       0 1244.39    18.8 1233.64    46.9 1217.22    56.3 1211.85    65.7 1208.13
      75 1203.85   103.2  1187.5   121.9  1172.4   140.7 1163.03   150.1 1158.54
   159.5 1154.83   168.8 1152.44   186.9 1151.17   204.9 1149.41     214 1148.73
   218.8 1148.19     232 1146.78   233.8 1146.82     241 1146.95     250 1148.73
   259.1 1154.06   268.6 1160.06   278.2 1163.19   287.7 1164.44   297.3  1164.6
   325.9  1164.6     345  1164.7   411.9 1164.53
#Mann= 3 , 0 , 0
       0     .06       0   218.8    .045       0   233.8     .06       0
Bank Sta=218.8,233.8
XS Rating Curve= 0 ,0
Exp/Cntr=0.3,0.1

Type RM Length L Ch R = 1 ,11.4    ,17.9,11.4,5
XS GIS Cut Line= 6
     1737901.775      310064.867     1737905.142      310062.382
     1738008.492      310056.522      1738109.44      309993.243
     1738218.775      309924.705     1738307.811      309787.264
#Sta/Elev= 30
       0 1158.39      23 1158.15    70.1 1156.22    79.5 1156.09    98.3 1156.81
   174.9 1150.96   184.5 1150.03   203.6 1143.29   211.4 1141.38   219.1 1140.33
   227.7 1140.44   232.8 1140.58   238.8 1141.89   242.7 1143.33   247.3 1145.03
   256.4 1149.33   265.4 1152.64   274.5 1153.72   292.6 1153.89   301.6 1153.47
   346.8 1156.05   355.9  1155.1   365.5 1155.65   384.8 1159.27   394.4  1160.6
     404 1161.21   413.7 1161.59   461.8 1161.44   500.4 1163.06   519.6 1163.39
#Mann= 3 , 0 , 0
       0     .06       0   227.7    .045       0   242.7     .06       0
Bank Sta=227.7,242.7
XS Rating Curve= 0 ,0
Exp/Cntr=0.3,0.1

Chan Stop Cuts=-1
Use User Specified Reach Order=0
Composite Channel Slope=5